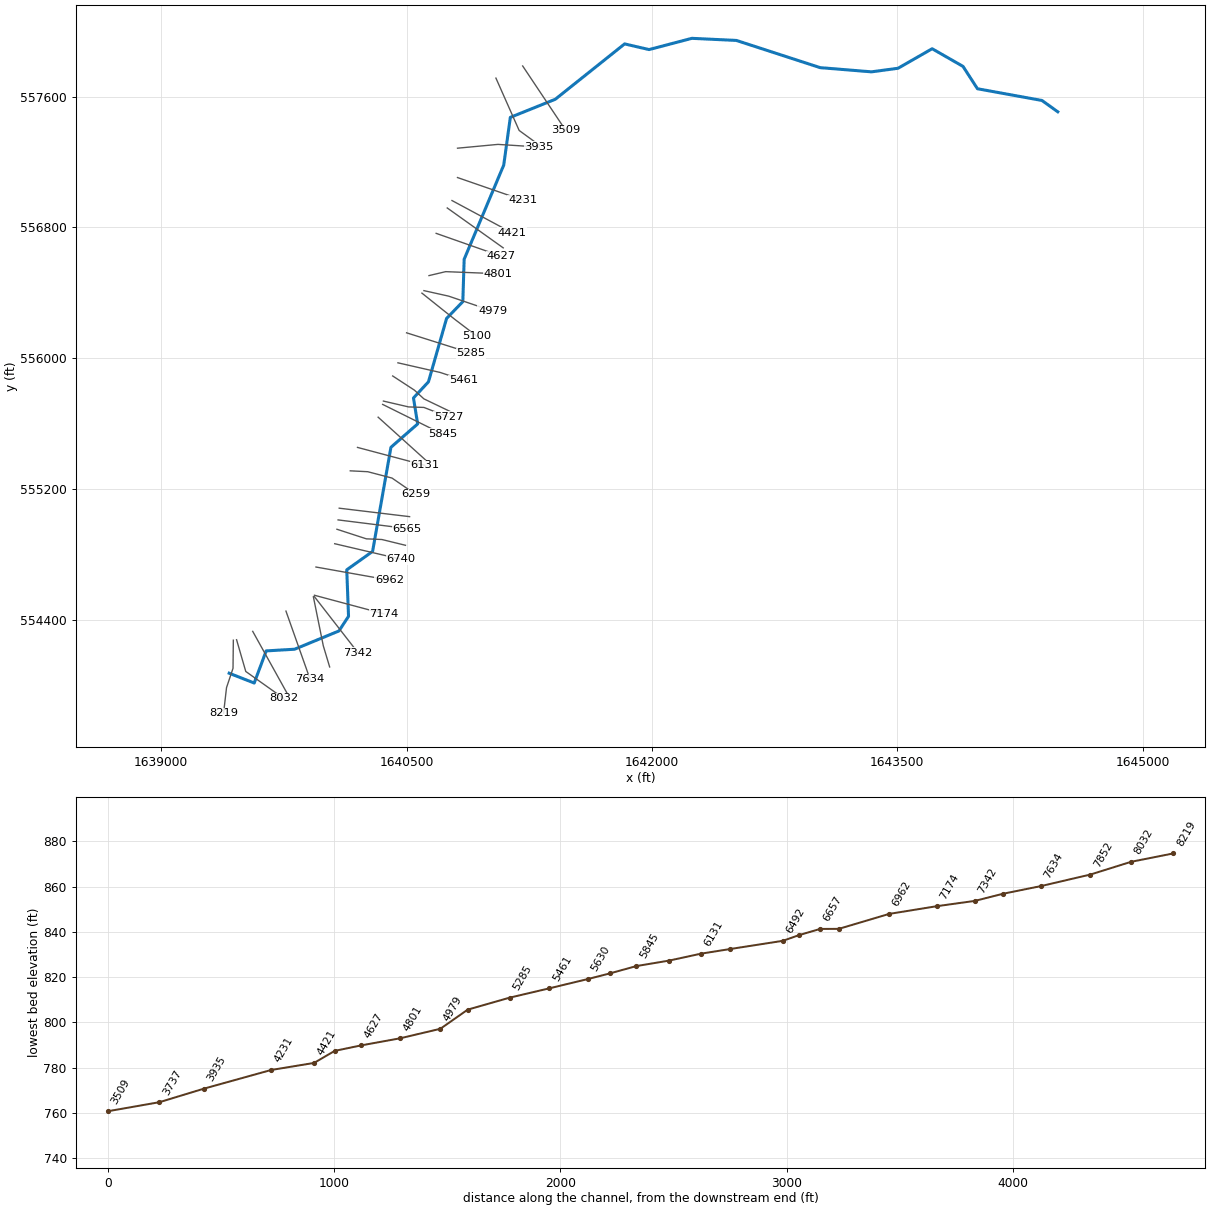
--- JakesRn.prj (project) ---

Proj Title=JakesRn
Current Plan=p01
Default Exp/Contr=0,0
English Units
Geom File=g01
Flow File=f01
Plan File=p01
BEGIN DESCRIPTION:
---------- MODELED AS PART OF WVEM CTP PROGRAM, 2025----------
Stream Name: Jakes Run
Flood Zone: AFH
Marshall County, WV
HEC-RAS Version: RAS 6.6
Vertical Datum: NAVD88
Projection: NAD 1983 StatePlane West Virginia N FIPS 4701 (US Feet)
Terrain: 1-meter West Virginia FEMA R3 South Central (collected 2018-2019)
Land Use: 2024 NLCD
Hydrologic Method:
Duda et al., "Estimation of magnitude and frequency of floods for rural, unregulated streams in and near Virginia and West Virginia." September 8, 2025.
Additional Model Notes:
None
END DESCRIPTION:
DSS Export Rating Curves= 0
DSS Export Rating Curve Sorted= 0
DSS Export Volume Flow Curves= 0
DXF OffsetX= 0
DXF OffsetY= 0
DXF ScaleX= 0
DXF ScaleY= 0

--- JakesRn.p01 (plan) ---

Plan Title=Floodplain
Program Version=6.60
Short Identifier=Floodplain
Geom File=g01
Flow File=f01
Subcritical Flow
K Sum by GR= 0
Std Step Tol= 0.01
Critical Tol= 0.01
Num of Std Step Trials= 20
Max Error Tol= 0.3
Flow Tol Ratio= 0.001
Split Flow NTrial= 30
Split Flow Tol= 0.02
Split Flow Ratio= 0.02
Log Output Level= 0
Friction Slope Method= 1
Unsteady Friction Slope Method= 2
Unsteady Bridges Friction Slope Method= 1
Parabolic Critical Depth
Global Vel Dist= 0 , 0 , 0
Global Log Level= 0
CheckData=False
Encroach Param=-1 ,0,0, 0
Flow Ratio Tolerance=0.1
Flow Ratio Min Ratio=0.5
Flow Ratio Max Ratio=4
Flow Ratio Max Iterations= 10
Mapping Interval=1HOUR
Computation Time Step Use Courant=        0
Computation Time Step Use Time Series=    0
Computation Time Step Count To Double=0
Computation Time Step Max Doubling=0
Computation Time Step Max Halving=0
Computation Time Step Residence Courant=0
Run HTab= 0
Run UNet= 0
Run Sediment= 0
Run PostProcess= 0
Run WQNet= 0
Run RASMapper=-1
UNET Theta= 0
UNET Theta Warmup= 0
UNET ZTol= 0
UNET ZSATol= 0
UNET MxIter= 0
UNET Max Iter WO Improvement= 0
UNET MaxInSteps= 0
UNET DtIC= 0
UNET DtMin= 0
UNET MaxCRTS= 0
UNET WFStab= 0
UNET SFStab= 0
UNET WFX= 1
UNET SFX= 1
UNET Gravity=32.17405
UNET 1D Methodology=Finite Difference
UNET DSS MLevel= 1
UNET Pardiso=0
UNET DZMax Abort= 0
UNET Use Existing IB Tables= 0
UNET Froude Reduction=False
UNET Froude Limit= 0
UNET Froude Power= 0
UNET D1 Cores= 0
UNET WindReference=Eulerian
UNET WindDragFormulation=Hsu (1988)
UNET D2 Coriolis=0
UNET D2 Cores= 0
UNET D2 Theta= 1
UNET D2 Theta Warmup= 1
UNET D2 Z Tol= 0.01
UNET D2 Volume Tol= 0.01
UNET D2 Max Iterations= 20
UNET D2 Advanced Convergence=0
UNET D2 WS Max Tol=0.15
UNET D2 WS RMS Tol=0.002
UNET D2 WS Stall Tol=1
UNET D2 Equation= 0
UNET D2 RampUpFraction=0.1
UNET D2 TimeSlices= 1
UNET D2 Turbulence Formulation=Non-Conservative (original)
UNET D2 Eddy Viscosity=0.3
UNET D2 Transverse Eddy Viscosity=0.1
UNET D2 Smagorinsky Mixing=0
UNET D2 BCVolumeCheck=0
UNET D2 Cores=0
UNET D2 SolverType=PARDISO (Direct)
UNET D2 Minimum Iterations= 3
UNET D2 Maximum Iterations= 30
UNET D2 Restart Number= 10
UNET D2 Relaxation Coeff=1.3
UNET D2 SOR Precondition Iterations= 10
UNET D2 ILUT Maximum Fill= 8
UNET D2 ILUT Tolerance=1E-08
UNET D2 Convergence Tolerance=0.00001
PS Theta= 1
PS WS Tol= 0.01
PS Volume Tol= 0.01
PS Max Iterations= 20
PS Equation= 0
PS Advance Time Step=-1
PS Target Courant=0.9
PS Time Slices= 1
PS Iterate With 2D=0
PS Project Initial WSE from DS=-1
PS Ramp Up Initial WSE from US=-1
PS Cores=0
UNET D1D2 MaxIter= 0
UNET D1D2 ZTol=0.01
UNET D1D2 QTol=0.1
UNET D1D2 MinQTol=1
Write IC File= 0
Write IC File at Fixed DateTime=0
Write IC File at Sim End=0
Echo Input=False
Echo Parameters=False
Echo Output=False
Write Detailed= 0
HDF Write Warmup=0
HDF Write Time Slices=0
HDF Flush=0
HDF Compression= 1
HDF Chunk Size= 1
HDF Spatial Parts= 1
HDF Use Max Rows=0
HDF Fixed Rows= 1
Calibration Method= 0
Calibration Iterations= 20
Calibration Max Change=0.05
Calibration Tolerance=0.2
Calibration Maximum=1.5
Calibration Minimum=0.5
Calibration Optimization Method= 1
WQ AD Non Conservative
WQ ULTIMATE=-1
WQ Max Comp Step=1HOUR
WQ Output Interval=15MIN
WQ Output Selected Increments= 0
WQ Create Restart=0
WQ Fixed Restart=0
WQ System Summary=0
WQ Write To DSS=0
Sorting and Armoring Iterations= 10
XS Update Threshold= 0.02
Bed Roughness Predictor= 0
Processes Affected by Predictor=Sediment Only
Hydraulics Update Threshold= 0.02
Energy Slope Method= 1
Volume Change Method= 1
Sediment Retention Method= 0
Sediment TS Multiplier= 1
Warm Up Method= 0
XS Weighting Method= 0
Number of US Weighted Cross Sections= 1
Number of DS Weighted Cross Sections= 1
Upstream XS Weight=0
Main XS Weight=1
Downstream XS Weight=0
Number of DS XS's Weighted with US Boundary= 1
Upstream Boundary Weight= 1
Weight of XSs Associated with US Boundary= 0
Number of US XS's Weighted with DS Boundary= 1
Downstream Boundary Weight= 0.5
Weight of XSs Associated with DS Boundary= 0.5
Percentile Method= 0
Sediment Output Level= 3
Mass or Volume Output= 0
Output Increment Type= 1
Profile and TS Output Increment= 1
Transport Output Increment 1
XS Output Flag= 0
XS Output Increment= 10
Read HDF5 Sediment Hotstart= 0
Sediment Hotstart Type= 0
Write Gradation File= 0
Read Gradation Hotstart= 0
Write HDF5 File= 1
Write Binary Output= 1
Write DSS Sediment File= 0
DSS Sediment Output Type= 1
SV Curve= 0
Specific Gage Flag= 0
Subcell Erosion Methods= 0
Subcell Deposition Methods= 0
Advection Scheme= 1
Matrix Solver= 0
Implicit Weighting Factor= 1
Maximum Outer Loop Convergence Iterations= 5
Convergence Maximum Absolute= 0.001
Convergence RMSE= 0.0001
Grain Fractions Max Abs Error= 0.001
Max Subgrid Regions= 1
Max Subgrid Length Scale= 3.402823E+38
Initial Layer Thickness= 3
Min Layer Thickness= 0.1
Max Layer Thickness= 6
Number of Layers= 5

--- JakesRn.f01 (steady flow) ---

Flow Title=Flow
Program Version=6.60
Number of Profiles= 1
Profile Names=P100yr
River Rch & RM=JakesRn,Main,8219
     856
River Rch & RM=JakesRn,Main,3737
    1010
River Rch & RM=JakesRn,Main,2987
    1160
Boundary for River Rch & Prof#=JakesRn,Main            , 1
Up Type= 0
Dn Type= 3
Dn Slope=0.0105
DSS Import GetInterval= 0
DSS Import GetPeak= 0
DSS Import FillOption= 0

--- JakesRn.g01 (geometry) ---

Geom Title=Geometry
Program Version=6.60

River Reach=JakesRn         ,Main
Reach XY= 30
      1639414.98      554074.079     1639568.079      554014.062
     1639641.284      554210.574     1639815.235      554220.787
     1640085.972      554332.346     1640144.727      554421.823
     1640133.915      554706.205     1640291.834      554818.648
     1640403.901      555455.162      1640567.33      555598.198
     1640541.808      555756.883     1640633.427      555855.558
     1640744.059       556242.77     1640843.441      556345.901
     1640851.716         556605.      1641093.56      557180.693
     1641133.928      557472.378     1641408.684      557583.062
     1641832.721      557921.573     1641982.283      557886.893
      1642243.76       557955.62      1642515.63      557942.876
     1643028.307      557776.408     1643342.164      557750.807
     1643504.307      557772.615     1643712.913       557892.09
     1643901.606      557783.994     1643989.789      557647.452
      1644384.13       557575.73     1644480.935      557506.427

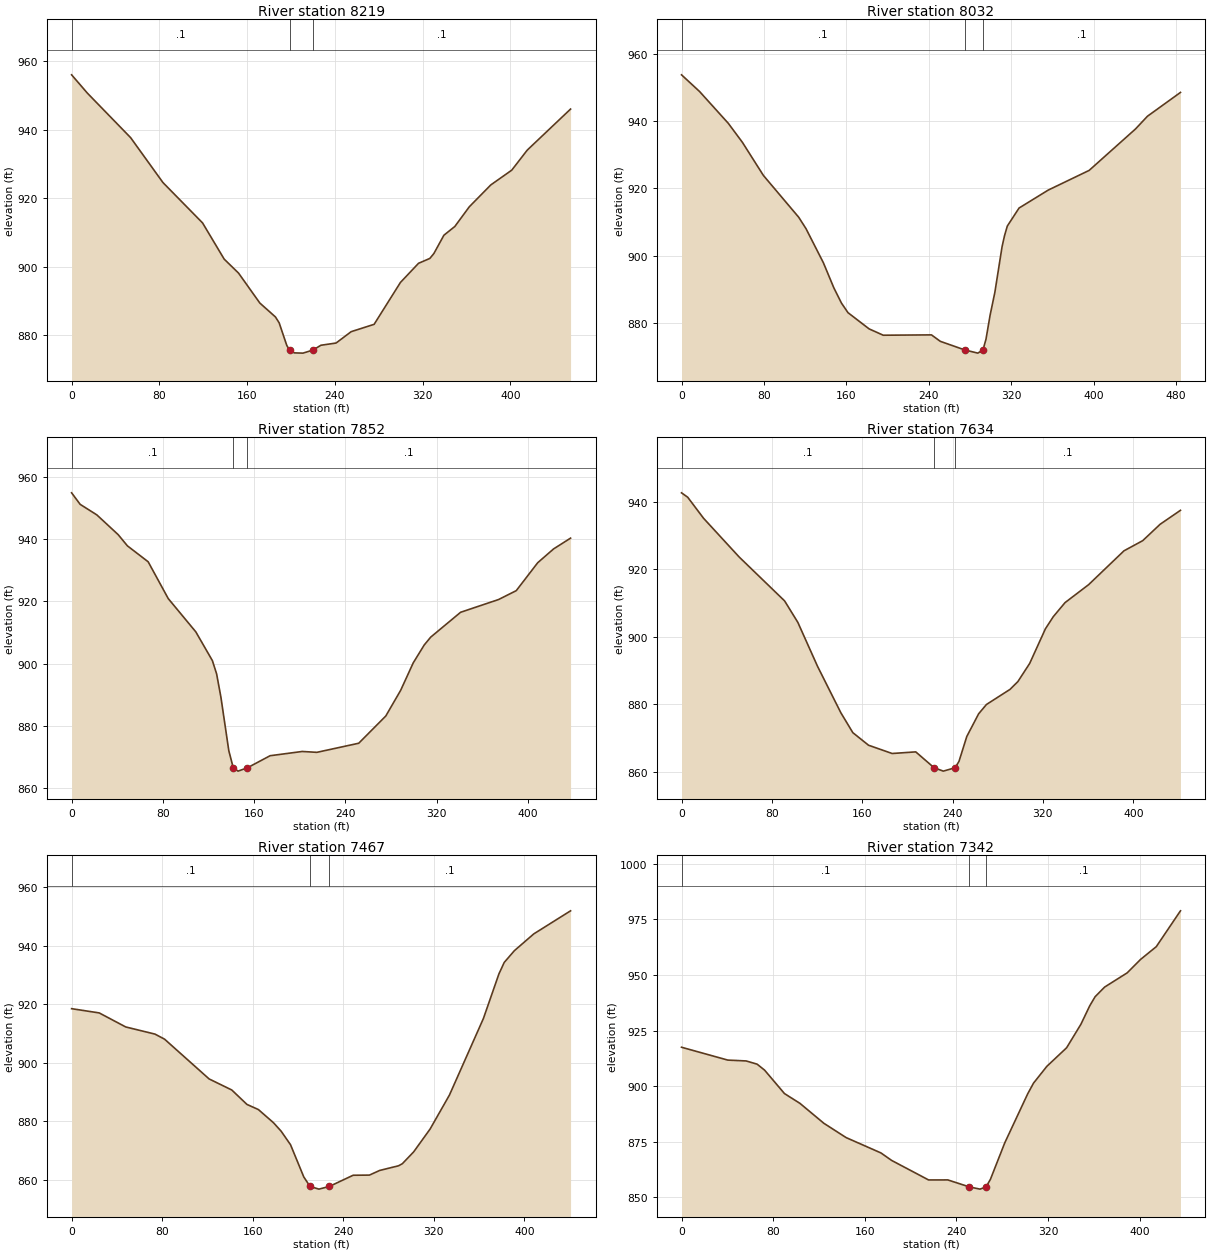
Type RM Length L Ch R = 1 ,8219    ,168.9,187.2,192.3
XS GIS Cut Line= 4
1639440.44191326554275.9059593011639438.51071052554104.267353156
1639398.81151803553986.0340068991639380.63482105553828.543919527
#Sta/Elev= 30
       0  956.06    14.4   950.7    53.8  937.69    83.3  924.55   119.4  912.75
   139.1  902.17   152.2  898.08   171.6  889.33   185.8  885.27   189.2  883.56
   196.2  876.91  198.75 875.565   203.1  874.75   210.9  874.68  219.92875.5638
   227.3  876.98   241.1  877.63   254.9  880.96   275.8   883.1   299.8  895.35
   316.3  900.95   326.6  902.37   330.3  903.81   339.4  909.15   349.4  911.72
   362.6  917.48   382.2  923.87   401.3  928.19   415.4  934.04   454.9  946.05
#Mann= 3 ,-1,0
       0      .1       0  198.75    .045       0  219.92      .1       0
Bank Sta=198.75,219.92
XS Rating Curve= 0 ,0
Exp/Cntr=0.3,0.1

Type RM Length L Ch R = 1 ,8032    ,177.1,179.7,174.2
XS GIS Cut Line= 3
1639460.23564389554278.8159557981639516.42081642554084.789826681
1639746.40545595553921.478258543
#Sta/Elev= 30
       0  953.81    17.5  948.85    45.4  939.37      59  933.75    79.5  923.84
   113.7  911.42   120.8  908.01   137.6   897.9   147.8   890.4   155.2  885.86
   161.5  883.02     182  878.19   195.7   876.3   242.5   876.4   251.1  874.48
  274.88 871.915   287.5  870.97  292.47871.9164   295.4  875.09   299.4  882.26
     304  889.03     311  902.63   313.4  905.93   316.1  908.79   327.5  914.16
   355.8   919.5   395.5  925.36   440.5   937.7   452.1  941.49   484.1  948.57
#Mann= 3 ,-1,0
       0      .1       0  274.88    .045       0  292.47      .1       0
Bank Sta=274.88,292.47
XS Rating Curve= 0 ,0
Exp/Cntr(USF)=0,0
Exp/Cntr=0.3,0.1

Type RM Length L Ch R = 1 ,7852    ,216.4,218.1,215.9
XS GIS Cut Line= 2
1639558.94548049554329.9790693181639771.24795855 553947.59933409
#Sta/Elev= 30
       0  954.97     7.5  951.26    22.1  947.87    40.8  941.51    48.9   937.9
    67.1  932.77    84.7  920.92   108.9  910.19   123.4  900.94   127.1  896.69
   130.9  889.13   137.8  871.94   141.7866.4211   145.9  865.35   154.1866.4225
     174  870.31   202.2  871.68     215   871.4   251.7  874.33   275.4  883.09
   288.5   891.4   299.5  900.23   309.1  905.96   314.8   908.5     341   916.5
   374.3  920.61   389.8  923.47   408.6  932.46   422.5   936.9   437.4  940.38
#Mann= 3 ,-1,0
       0      .1       0   141.7    .045       0   154.1      .1       0
Bank Sta=141.7,154.1
XS Rating Curve= 0 ,0
Exp/Cntr(USF)=0,0
Exp/Cntr=0.3,0.1

Type RM Length L Ch R = 1 ,7634    ,165.9,167.8,164
XS GIS Cut Line= 2
1639762.21669898554453.7126690441639909.59895014554037.212189718
#Sta/Elev= 30
       0  942.67     5.5  941.36    19.5  935.14    51.1  923.65    91.3  910.66
     103  904.31   120.4  891.32   141.1  877.54   151.7  871.65   165.6  867.93
   186.5  865.48   207.4  865.96  223.63861.2698   231.8  860.26  242.33861.2696
   245.7  863.16   252.6  870.52   263.1  877.24     270  879.99   290.9  884.47
   297.8  886.76   308.3  892.16   322.2  902.39   329.2     906   339.6  910.16
   360.5  915.48   391.8   925.5   408.4  928.51   423.8  933.36   441.8  937.49
#Mann= 3 ,-1,0
       0      .1       0  223.63    .045       0  242.33      .1       0
Bank Sta=223.63,242.33
XS Rating Curve= 0 ,0
Exp/Cntr(USF)=0,0
Exp/Cntr=0.3,0.1

Type RM Length L Ch R = 1 ,7467    ,120.3,124.6,126.5
XS GIS Cut Line= 3
1639929.81634856554541.2856522621639990.34824396554241.984446772
1640029.34657658554112.298642839
#Sta/Elev= 30
       0   918.5    24.4  917.05    47.8  912.26    73.7  909.81    82.1  908.09
   121.5   894.5   141.5  890.73   154.9   885.8     165  884.05   178.4  879.53
   185.1  876.66   193.4  872.04   205.1  861.04  210.63857.7903   218.5  856.87
  227.71857.7903   248.7  861.61   263.1  861.66   272.1  863.24   288.8  864.84
   292.2  865.55   302.2   869.6   316.7  877.39   333.8     889   363.8  915.14
   377.5  930.36   382.2   934.3   391.2  938.32   408.3  944.04   440.8  951.92
#Mann= 3 ,-1,0
       0      .1       0  210.63    .045       0  227.71      .1       0
Bank Sta=210.63,227.71
XS Rating Curve= 0 ,0
Exp/Cntr(USF)=0,0
Exp/Cntr=0.3,0.1

Type RM Length L Ch R = 1 ,7342    ,162.7,168.2,172.9
XS GIS Cut Line= 2
1639935.18763563554543.2608344791640202.62905685 554199.40757863
#Sta/Elev= 30
       0  917.52    40.4  911.74    56.4  911.36      66  909.91    72.5  907.24
    89.9  896.68   103.4  892.28   124.2  883.35   143.7  876.89   174.1  869.99
   183.4  866.63   215.7  857.84   232.5  857.85  251.34854.7031   260.6  853.71
  265.93854.7032   269.7  858.13   282.2  874.52   302.2  896.54   307.3  901.37
     319  908.96   336.2  917.28   348.7  927.87   356.4  936.16   361.1  940.25
   369.4  944.58   389.1  950.98   400.8  957.03   414.5  962.76   435.6  978.87
#Mann= 3 ,-1,0
       0      .1       0  251.34    .045       0  265.93      .1       0
Bank Sta=251.34,265.93
XS Rating Curve= 0 ,0
Exp/Cntr(USF)=0,0
Exp/Cntr=0.3,0.1

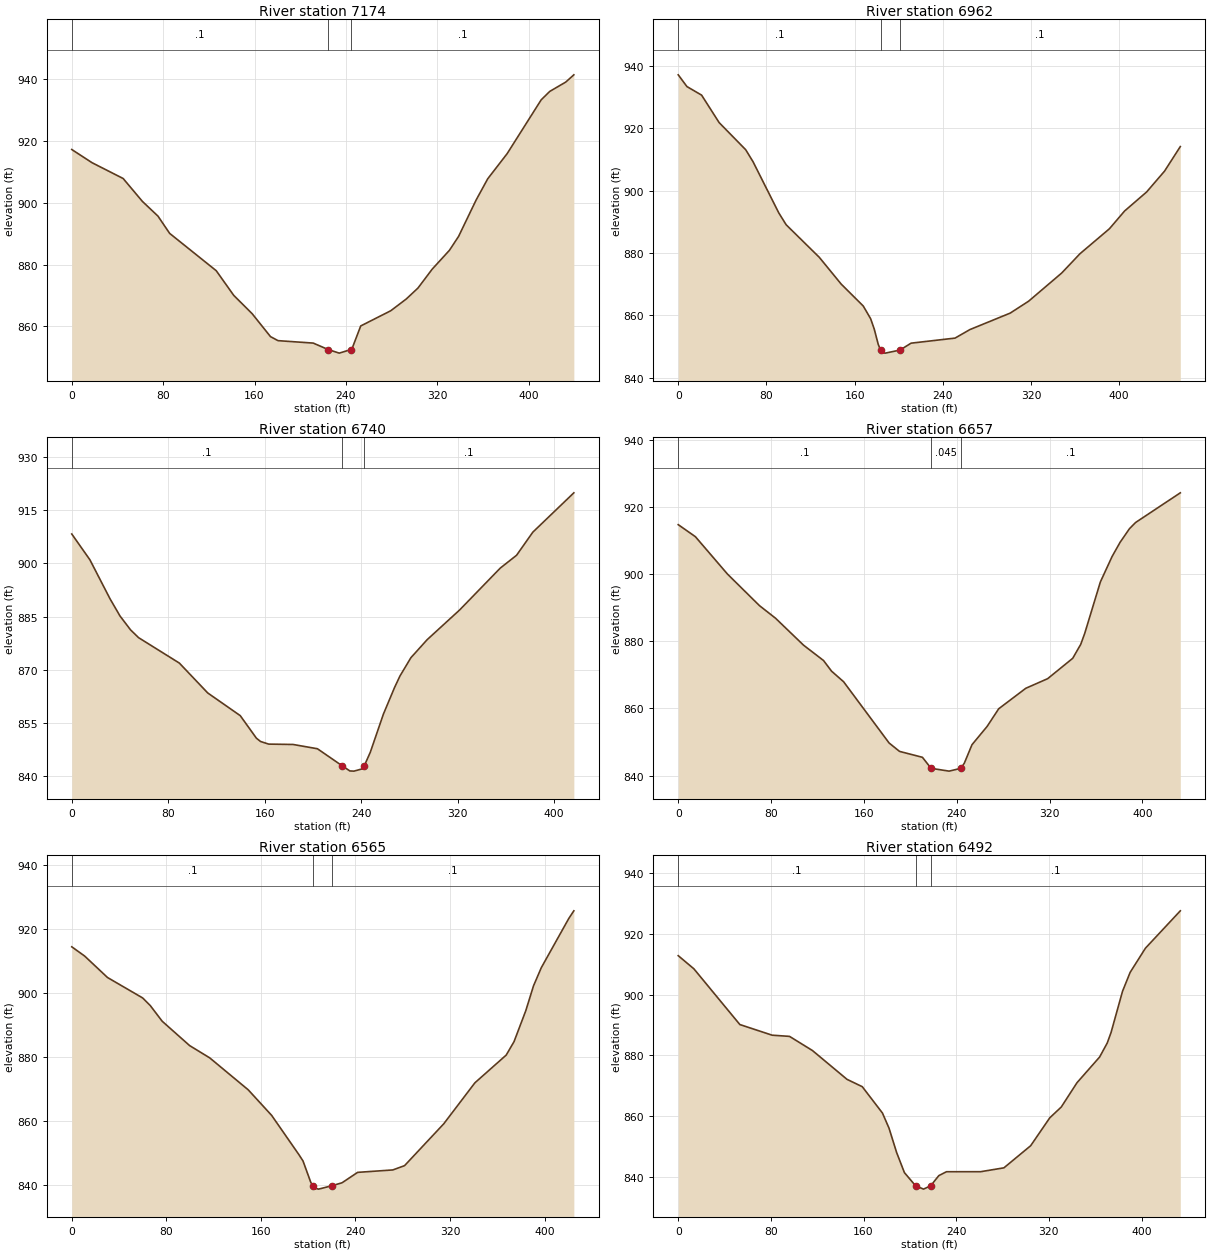
Type RM Length L Ch R = 1 ,7174    ,207.1,211.3,209.1
XS GIS Cut Line= 2
1639936.23607159554550.7547129991640360.92815181554437.124840599
#Sta/Elev= 30
       0  917.29    17.8  913.01      45   907.9    61.9  900.47    75.5  895.72
    85.7  890.14   126.5  878.05   141.8  870.08     158  864.11     174  856.71
   180.6  855.41   211.4  854.62  224.58852.5208   234.2  851.37  244.37852.5208
   246.1  853.49     253  860.17   279.3  865.09   292.9   868.9   303.1  872.43
   315.6  878.56   330.7  884.67   338.7  889.17     354  900.91   364.2  907.81
   381.2  915.95     411  933.37   418.5   936.1   432.5  939.12   439.6  941.47
#Mann= 3 ,-1,0
       0      .1       0  224.58    .045       0  244.37      .1       0
Bank Sta=224.58,244.37
XS Rating Curve= 0 ,0
Exp/Cntr(USF)=0,0
Exp/Cntr=0.3,0.1

Type RM Length L Ch R = 1 ,6962    ,215,222.4,213.7
XS GIS Cut Line= 2
1639945.65739108554723.2859994121640394.03091136 554643.57293022
#Sta/Elev= 30
       0  937.04     7.9  933.28    21.2  930.54    37.1  921.75    61.2  913.06
    67.9  909.19    91.2  892.84    97.9  889.04   127.9  878.64   147.8  870.05
   167.8  863.04   174.5  858.98   177.8  855.64   181.4  850.77  183.51848.9292
   184.5  848.06   187.8  847.95  201.16 848.928   211.2  851.14   251.1  852.76
   264.5  855.48   301.1  860.76   317.8  864.57   347.8  873.59   364.4  879.77
   391.1  887.76   404.9  893.46   424.8  899.52   441.1  906.21   455.4  914.07
#Mann= 3 ,-1,0
       0      .1       0  183.51    .045       0  201.16      .1       0
Bank Sta=183.51,201.16
XS Rating Curve= 0 ,0
Exp/Cntr(USF)=0,0
Exp/Cntr=0.3,0.1

Type RM Length L Ch R = 1 ,6740    ,80.1,82.5,84
XS GIS Cut Line= 2
1640060.21004916554865.8145920031640465.57566426554770.924078407
#Sta/Elev= 30
       0  908.33      15  901.07    31.7  890.04      40  885.17    48.7  881.27
    55.4  879.05    89.2  871.87   112.7  863.44   139.7  857.02   153.1  850.65
   156.5  849.73   163.3  848.98   183.5  848.88   203.7  847.67  224.26842.8431
   230.6   841.4     234  841.35   240.8  841.99  242.52842.8426   247.5  846.65
   258.4  857.46   267.7  865.01   272.1   868.2   281.2  873.39   294.7  878.49
   321.6  886.87   355.3   898.7   368.8  902.32   382.3  908.85   416.3  919.96
#Mann= 3 ,-1,0
       0      .1       0  224.26    .045       0  242.52      .1       0
Bank Sta=224.26,242.52
XS Rating Curve= 0 ,0
Exp/Cntr(USF)=0,0
Exp/Cntr=0.3,0.1

Type RM Length L Ch R = 1 ,6657    ,92,92.1,91.4
XS GIS Cut Line= 4
1640073.84968498554954.2123999021640253.81796023554895.613345892
1640348.75058263554891.5102525241640492.81072454554856.177366362
#Sta/Elev= 30
       0  914.79    14.8   911.2    42.4  900.07      70  890.65    83.8  886.91
     108  878.86   125.2  874.29   132.1  871.12   142.5  867.96   181.7   849.7
   190.7   847.2   210.4  845.44  217.85842.1545   233.4  841.32  243.52842.1525
   246.5  843.69   253.1  849.19   266.2  854.67   276.1   859.9   299.5  866.02
   318.3  868.88   339.9  874.95   346.8  879.11   350.2  882.33   363.7  897.69
   373.8  905.28   380.7  909.52   388.8  913.59   394.1  915.44   432.6  924.28
#Mann= 3 ,-1,0
       0      .1       0  217.85    .045       0  243.52      .1       0
Bank Sta=217.85,243.52
XS Rating Curve= 0 ,0
Exp/Cntr(USF)=0,0
Exp/Cntr=0.3,0.1

Type RM Length L Ch R = 1 ,6565    ,73,73.1,73.2
XS GIS Cut Line= 2
 1640080.8966995555011.3378790451640502.28549344554958.748557562
#Sta/Elev= 30
       0  914.39    10.9   911.5    30.2   904.8      60  898.39    66.4  896.02
    76.5  891.11    99.7   883.5   116.7  879.66   149.3  869.66   169.1  861.67
   192.2  849.37   195.6  847.43   202.2  840.72  203.99839.7051   205.5  838.91
   208.8  838.62  220.28 839.706   228.6   840.6   241.8  843.86   271.6  844.62
   281.5  845.96   314.6  859.02     341  871.86   367.5  880.54   374.1  884.73
     384  894.36   390.6   902.2   397.2  907.88   420.4  923.23   424.7  925.64
#Mann= 3 ,-1,0
       0      .1       0  203.99    .045       0  220.28      .1       0
Bank Sta=203.99,220.28
XS Rating Curve= 0 ,0
Exp/Cntr(USF)=0,0
Exp/Cntr=0.3,0.1

Type RM Length L Ch R = 1 ,6492    ,234.1,233.5,232.8
XS GIS Cut Line= 2
1640087.64592756555083.0333589841640518.06077603555031.290190851
#Sta/Elev= 30
       0  912.81    13.5   908.5    53.2  890.17    81.1  886.67    96.1  886.28
   115.9  881.62   145.7  872.16   158.9  869.74   176.3  861.09     182   856.1
   188.6  848.06   195.3  841.48  204.93837.1581   211.8  836.06  217.96837.1573
     225   840.5   231.6  841.78   261.1  841.79   281.2  843.06   304.3  850.33
   320.8  859.51   330.7  863.05   344.3  871.05   363.8  879.48   370.4  884.09
   373.7  887.55   383.6   901.1   390.2  907.33   403.4  915.28   433.5  927.56
#Mann= 3 ,-1,0
       0      .1       0  204.93    .045       0  217.96      .1       0
Bank Sta=204.93,217.96
XS Rating Curve= 0 ,0
Exp/Cntr(USF)=0,0
Exp/Cntr=0.3,0.1

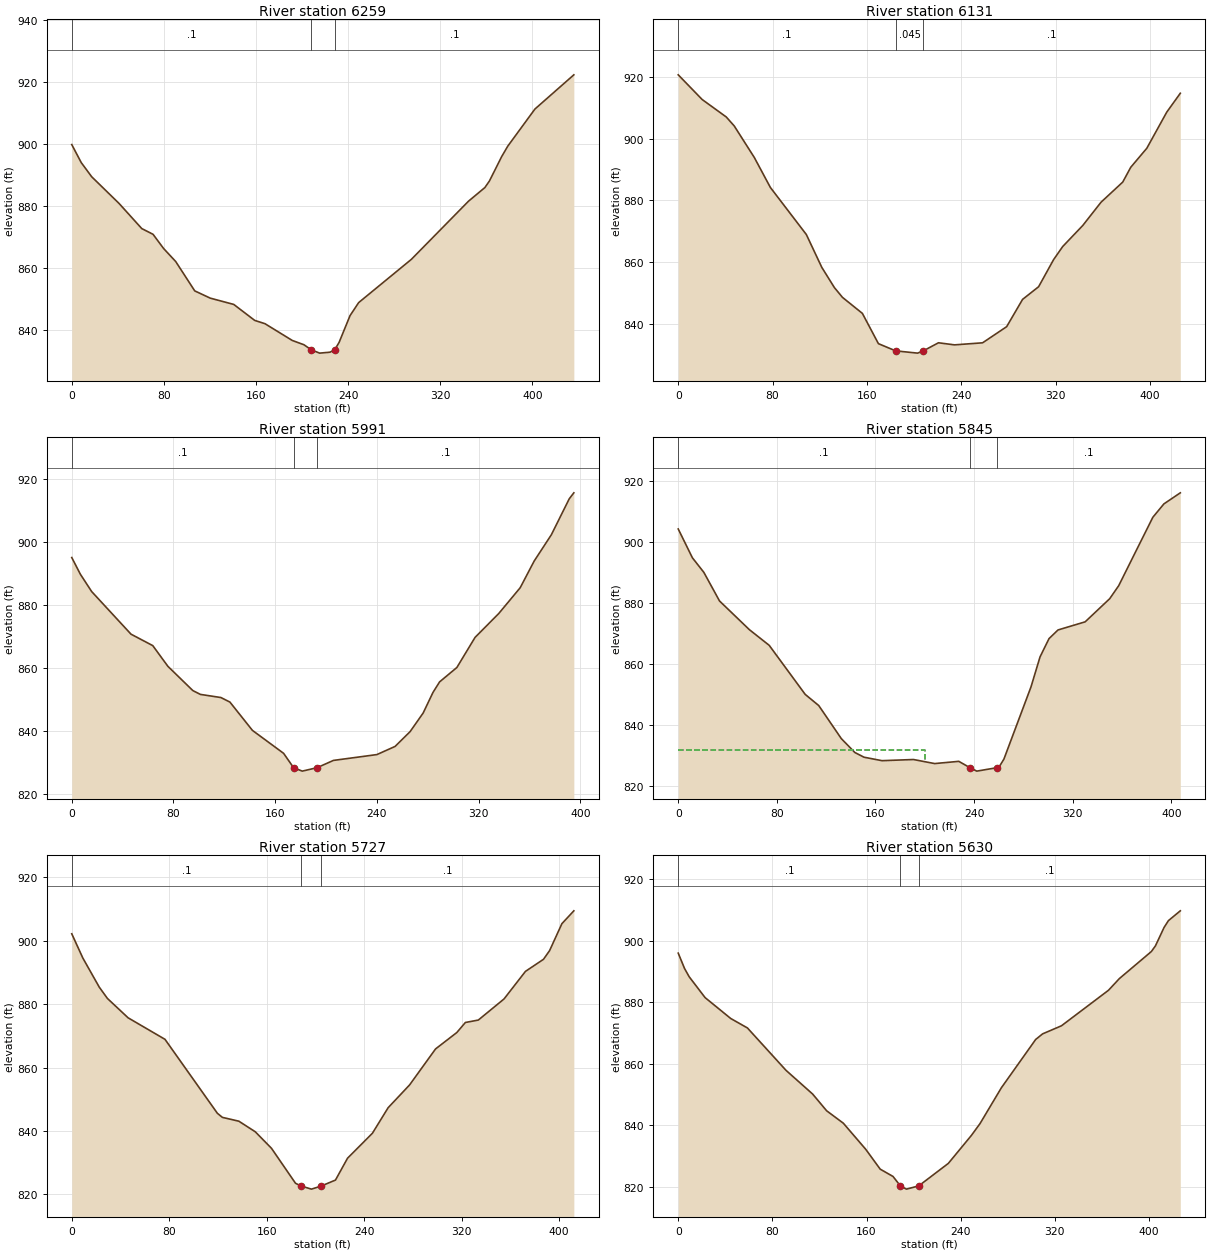
Type RM Length L Ch R = 1 ,6259    ,128.1,127.6,127.7
XS GIS Cut Line= 4
1640155.19560742555311.4175617551640262.14408728555306.035540884
1640410.57821679555267.2143070111640555.07833783555167.476576671
#Sta/Elev= 30
       0  899.79     8.2  893.99    17.3   889.4    41.1  880.77    60.8  872.66
    70.6  870.81    79.8  866.21    90.3  862.01   106.8  852.54   120.3  850.19
   140.7  848.16   158.9     843   167.8  841.94   191.5  836.53   201.7  835.13
     208833.5059   215.3  832.43   224.3  832.73  228.36833.5057   232.2  835.89
   241.7  844.54   249.2  848.75     295  862.73   344.6   881.5   358.8   885.9
   362.8  888.04   373.4   895.9   378.7  899.27   402.3  911.27   436.1  922.32
#Mann= 3 ,-1,0
       0      .1       0     208    .045       0  228.36      .1       0
Bank Sta=208,228.36
XS Rating Curve= 0 ,0
Exp/Cntr(USF)=0,0
Exp/Cntr=0.3,0.1

Type RM Length L Ch R = 1 ,6131    ,145.1,139.9,135.5
XS GIS Cut Line= 2
1640199.50611694555454.6105371561640610.78157982555345.236734643
#Sta/Elev= 30
       0  920.75    20.3  912.73    40.7  907.07    47.5  904.14    64.5  893.91
    78.1  884.19   108.6   868.9   121.7  858.24   132.4  851.67   139.2  848.51
   156.1   843.3   169.7  833.47  184.31831.1315   202.9   830.4  207.73831.1326
   220.6  833.76   234.2  833.08     258  833.75   278.4  838.99   291.9  847.85
   305.5  851.96   318.2  860.76   325.9     865   342.9  871.83   358.4  879.39
   376.8  885.93   383.6  890.74   397.2  896.91   414.1  908.63   425.6  914.77
#Mann= 3 ,-1,0
       0      .1       0  184.31    .045       0  207.73      .1       0
Bank Sta=184.31,207.73
XS Rating Curve= 0 ,0
Exp/Cntr(USF)=0,0
Exp/Cntr=0.3,0.1

Type RM Length L Ch R = 1 ,5991    ,144.3,146.2,150.6
XS GIS Cut Line= 2
1640325.64334968555639.4529171661640618.82341389555374.926116606
#Sta/Elev= 30
       0  894.98     6.8  889.67    15.7  884.19    46.6  870.72    63.7   867.1
    75.6  860.55    95.2  852.87   101.2  851.65   117.3  850.66   124.4  849.22
   142.1  840.26   166.6     833  174.48828.4439   181.3  827.36  192.92828.4455
   205.8  830.75     240   832.6   254.3  835.18   266.1  839.86   276.4  845.77
   284.1  852.27   289.3  855.61   302.9  860.17   317.2   869.7   335.8  877.24
   352.7  885.42   363.7  893.87   377.2  902.19   391.3  913.59   394.9  915.47
#Mann= 3 ,-1,0
       0      .1       0  174.48    .045       0  192.92      .1       0
Bank Sta=174.48,192.92
XS Rating Curve= 0 ,0
Exp/Cntr(USF)=0,0
Exp/Cntr=0.3,0.1

Type RM Length L Ch R = 1 ,5845    ,113.1,118.3,123.2
XS GIS Cut Line= 2
1640353.22874897555717.5571445711640718.13271612555536.565975478
#Sta/Elev= 30
       0  904.39    11.5  894.93    20.8  890.14    33.5  880.76    57.7  871.35
    73.8   866.2     103   850.1     114  846.43   132.3  835.58   143.3  831.02
   150.7  829.48   165.3  828.34   190.8  828.72     208  827.39   227.6  828.12
  236.73826.0242   242.2  824.91  258.35 826.023   260.5  826.41   264.2  828.85
   286.2  852.59   293.5   862.4   300.8  868.41   308.1  871.25   330.1  873.91
     350   881.5   357.3  885.76     385  908.22     394  912.63   407.3  916.26
#Mann= 3 ,-1,0
       0      .1       0  236.73    .045       0  258.35      .1       0
#XS Ineff= 2 , 0
          200.36  831.73
Permanent Ineff=
       F       F
Bank Sta=236.73,258.35
XS Rating Curve= 0 ,0
Exp/Cntr(USF)=0,0
Exp/Cntr=0.3,0.1

Type RM Length L Ch R = 1 ,5727    ,100.9,97.2,89.1
XS GIS Cut Line= 4
1640357.94054127555737.8960629781640512.06770654555702.094871045
1640605.51488548555699.0608717291640754.78765185555640.808084855
#Sta/Elev= 30
       0  902.23     9.1  894.57    22.6  885.37    29.3  881.81    46.2  875.72
    76.5  868.92   119.5  845.57   123.6  844.29   137.1  843.08   150.6  839.74
   163.9  834.52   183.6  823.49  188.28822.6118   196.7  821.64  204.66822.6115
   216.4   824.5   226.3   831.4   246.7  839.27   259.6  847.33   277.2  854.52
   298.5  865.88     316  871.08     323  874.24   333.6     875   354.7  881.66
   372.3  890.37   387.1  894.18   392.1  896.92   402.2  905.43     412  909.48
#Mann= 3 ,-1,0
       0      .1       0  188.28    .045       0  204.66      .1       0
Bank Sta=188.28,204.66
XS Rating Curve= 0 ,0
Exp/Cntr(USF)=0,0
Exp/Cntr=0.3,0.1

Type RM Length L Ch R = 1 ,5630    ,165.3,168.8,172.4
XS GIS Cut Line= 4
1640414.75386687555891.4003624121640547.39496645555804.770016769
1640605.45297806555751.4315596531640776.14275918555669.492314048
#Sta/Elev= 30
       0   895.9     5.4  890.88     9.3  888.22    22.8  881.45    44.6  874.65
    58.8  871.57    91.6  857.78   114.2  850.08   126.1  844.64   140.3  840.59
   159.3  832.12   171.6  825.66   182.5  823.28  188.75820.2084   193.9  819.16
  204.33 820.209   229.5  827.53   249.1  836.63   256.4  840.46   274.6  852.14
   303.7  867.82   309.6  869.65   325.6  872.27   365.6  883.83   374.8  887.62
     402  896.42   405.5  898.29   412.8  904.25   416.5  906.47   426.6  909.66
#Mann= 3 ,-1,0
       0      .1       0  188.75    .045       0  204.33      .1       0
Bank Sta=188.75,204.33
XS Rating Curve= 0 ,0
Exp/Cntr(USF)=0,0
Exp/Cntr=0.3,0.1

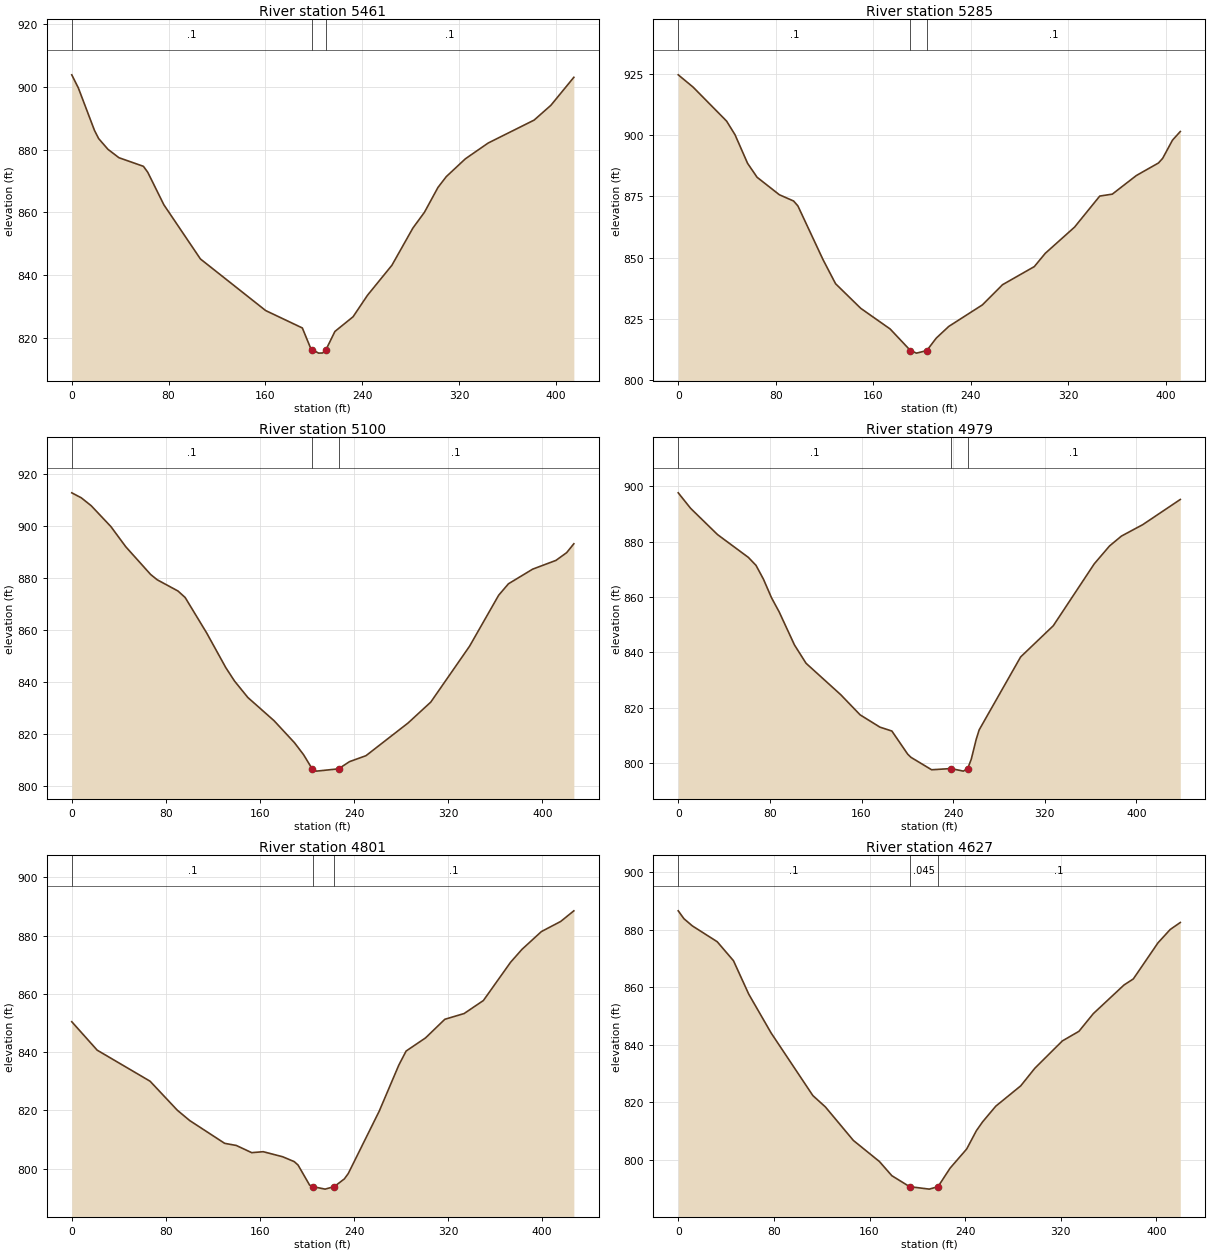
Type RM Length L Ch R = 1 ,5461    ,176.5,176.1,175.4
XS GIS Cut Line= 3
1640446.85340683555971.7759563751640704.60482485555912.970672881
1640847.42710364555865.776692724
#Sta/Elev= 30
       0  903.82     5.4  899.67    18.8  886.07    22.2   883.5    29.9  880.07
      39  877.39    59.2  874.65    62.8  872.74    76.1  862.38   106.3  845.11
   160.2  828.66   190.5  823.11   197.2   816.8  198.62816.2362   203.9  815.09
   207.3  815.14  210.09816.2343   217.4     822   232.4  826.68   244.3  833.53
   264.5  843.11   281.8  854.95   291.4  860.01   302.5  867.89   309.4  871.36
   325.2  877.05     344  882.07     382  889.39   395.8  894.09   414.8  903.03
#Mann= 3 ,-1,0
       0      .1       0  198.62    .045       0  210.09      .1       0
Bank Sta=198.62,210.09
XS Rating Curve= 0 ,0
Exp/Cntr(USF)=0,0
Exp/Cntr=0.3,0.1

Type RM Length L Ch R = 1 ,5285    ,187.7,185,180.4
XS GIS Cut Line= 2
1640499.55391633556155.2211598551640892.43393753556031.197593839
#Sta/Elev= 30
       0  924.65    12.2  919.63    39.7  905.74    46.6  900.17    56.9   888.5
    64.7   882.8      83  875.65    94.7  873.09    98.2  871.09   118.8  849.16
   129.1  839.31   149.8  829.24   173.9  820.81  190.58811.9928   195.5  810.95
  203.96811.9896   211.7  817.07     222  821.86   249.6  830.66   266.1   838.9
   292.2   846.3   301.2  851.73   325.2  862.42   345.9  875.12   356.2   875.9
   375.9   883.5   394.1  888.64   397.5  890.52   405.6  897.97     412  901.49
#Mann= 3 ,-1,0
       0      .1       0  190.58    .045       0  203.96      .1       0
Bank Sta=190.58,203.96
XS Rating Curve= 0 ,0
Exp/Cntr(USF)=0,0
Exp/Cntr=0.3,0.1

Type RM Length L Ch R = 1 ,5100    ,117.3,121.1,121.4
XS GIS Cut Line= 6
1640593.39486226 556397.886517421640661.72149725 556343.22652176
1640720.28699693556296.3749094161640798.65724701556234.259220004
 1640858.5370485 556188.803274171640929.36728743556134.683959842
#Sta/Elev= 30
       0  912.77     8.1  910.85    16.5  907.82    33.3  899.76    45.9  892.02
      67  881.37    72.6  879.32    90.3  874.98    96.4  872.48   114.7  858.82
     131  845.45   138.4  840.31   149.7     834     172  825.06   189.4  816.56
   197.1  811.96  204.35806.5485     208  805.67  226.77806.5484   236.1  809.32
   250.1  811.61   285.9   824.2   305.2  832.24   338.2  853.77   362.9  873.37
   371.2  877.76   391.8   883.4   411.6  886.77   420.7  889.75   426.8  893.17
#Mann= 3 ,-1,0
       0      .1       0  204.35    .045       0  226.77      .1       0
Bank Sta=204.35,226.77
XS Rating Curve= 0 ,0
Exp/Cntr(USF)=0,0
Exp/Cntr=0.3,0.1

Type RM Length L Ch R = 1 ,4979    ,174.5,177.8,178.8
XS GIS Cut Line= 3
1640605.61237747556413.1527203881640756.62147376556379.499050605
1641025.12833232556288.296781445
#Sta/Elev= 30
       0  897.57    10.8  891.98    34.3  882.51    61.2  874.29    67.9  871.41
    74.4  866.42    81.4  859.75    88.1  854.63   101.5  842.68   111.6  836.09
   141.9  824.75   158.8  817.49   176.1  813.06   186.5  811.66   200.4  803.27
   203.2  802.17   221.2  797.69  238.08  798.13   248.9   797.2  252.66798.1301
   255.8  801.47   260.1  808.63   262.7  812.07   298.9  838.38   327.4  849.63
   363.2  871.97   376.5   878.4   386.9  881.97   405.5  886.09   438.3  895.18
#Mann= 3 ,-1,0
       0      .1       0  238.08    .045       0  252.66      .1       0
Bank Sta=238.08,252.66
XS Rating Curve= 0 ,0
Exp/Cntr(USF)=0,0
Exp/Cntr=0.3,0.1

Type RM Length L Ch R = 1 ,4801    ,177.2,173.7,171.1
XS GIS Cut Line= 3
 1640636.6083585556505.0549382571640738.73398455556529.215405526
1641060.40311459556516.387884249
#Sta/Elev= 30
       0  850.44    21.6  840.69    66.6  830.03    89.7   820.1   100.3  816.53
     130  808.72   139.9  807.99     153  805.52   162.8  805.85   179.3  804.12
   189.1  802.46   192.4  801.28   202.2  794.41  204.89793.8801   215.4  793.01
  223.22793.8789   231.8  796.53   235.1  798.36   261.4  819.74   278.1  835.58
   284.3  840.39   300.8  844.89   317.2  851.28   333.6  853.25     350  857.72
   373.1  870.84   382.8  875.27   399.3  881.37   415.7  884.84   426.9  888.49
#Mann= 3 ,-1,0
       0      .1       0  204.89    .045       0  223.22      .1       0
Bank Sta=204.89,223.22
XS Rating Curve= 0 ,0
Exp/Cntr(USF)=0,0
Exp/Cntr=0.3,0.1

Type RM Length L Ch R = 1 ,4627    ,115.8,115.2,109.5
XS GIS Cut Line= 2
1640680.50213374556763.2846097621641076.70707945556623.984888216
#Sta/Elev= 30
       0  886.51     4.8  883.76    11.8  881.28    32.6  875.78    46.2  869.19
      59  857.56    77.8  844.02   112.6  822.35   123.1   818.4   146.5  806.76
   168.3  799.44   178.7  794.51  193.53790.7117     210  789.85  217.33790.7112
   227.4  797.13   241.3  803.79   249.4  810.14   254.6  813.21   265.6  818.65
   286.5  825.72   298.3  831.83   321.3  841.32   335.2  844.66   347.2  850.79
   372.9  860.75   380.7  862.86   401.3  875.38   411.5  880.01     420  882.46
#Mann= 3 ,-1,0
       0      .1       0  193.53    .045       0  217.33      .1       0
Bank Sta=193.53,217.33
XS Rating Curve= 0 ,0
Exp/Cntr(USF)=0,0
Exp/Cntr=0.3,0.1

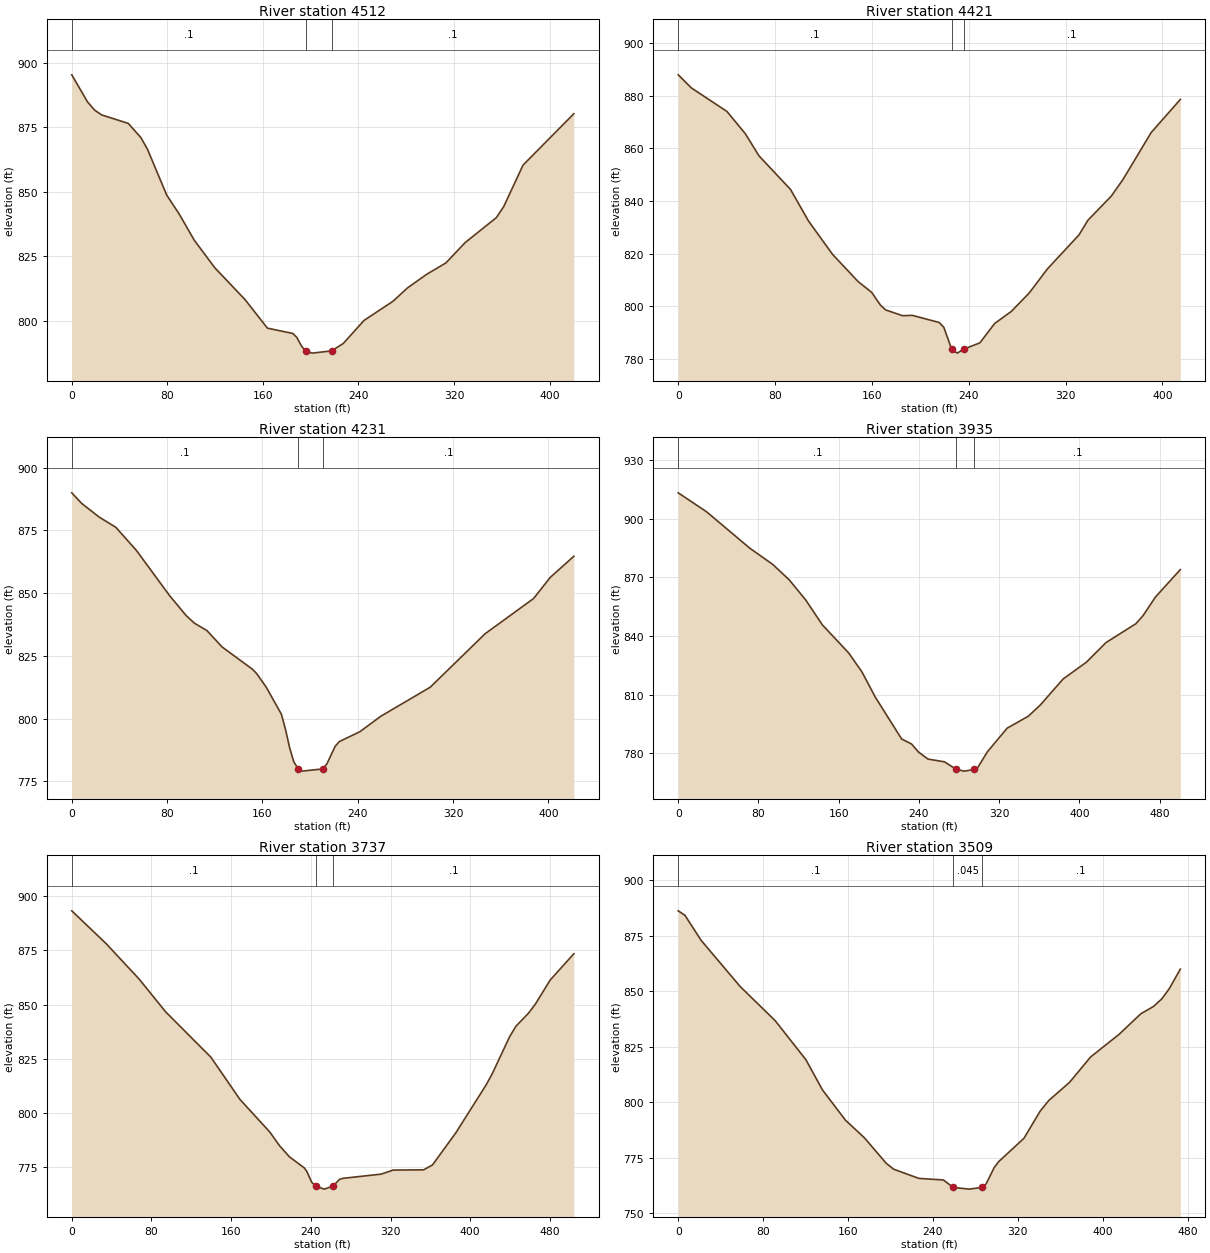
Type RM Length L Ch R = 1 ,4512    ,90.3,91.4,88.4
XS GIS Cut Line= 2
1640748.21996022556918.547830154 1641090.4550831556674.614285122
#Sta/Elev= 30
       0  895.33    13.2  884.84    19.1  881.66      25   879.8    47.3   876.5
    57.9  870.98    63.4  866.47    79.5   848.7    89.8  841.48   102.6  831.19
   119.8  820.52     145  808.24   163.8  797.14     185  795.08   188.3  793.61
   192.4  790.14  195.71 788.334   201.4  787.46  217.48 788.332   227.3  791.21
   244.7  800.15   268.9  807.56     281  812.72   297.1  818.01   313.2  822.42
   329.3   830.3   355.5  840.01   361.6  844.27   377.8  860.36   420.3  880.25
#Mann= 3 ,-1,0
       0      .1       0  195.71    .045       0  217.48      .1       0
Bank Sta=195.71,217.48
XS Rating Curve= 0 ,0
Exp/Cntr(USF)=0,0
Exp/Cntr=0.3,0.1

Type RM Length L Ch R = 1 ,4421    ,189.7,189.5,188.7
XS GIS Cut Line= 2
1640777.20814292556963.9099916671641142.69368443 556767.67302748
#Sta/Elev= 30
       0  887.98    10.8  883.02    40.3  874.03    55.5  865.54    66.7  857.17
    92.8  844.37   107.6   832.4   127.5  819.69   148.6  809.35   159.8  805.25
   167.2   800.3   171.4  798.55   185.3  796.37   193.3   796.5   215.6  793.79
   219.4  791.97   225.9 783.635   230.5  782.13  235.77783.6308   249.2  786.03
   261.5  793.44   275.2     798   290.1  805.07     305  814.16   331.1   827.1
   338.5  832.69   357.7  841.81   367.4  848.15   390.7  866.01   414.8  878.62
#Mann= 3 ,-1,0
       0      .1       0   225.9    .045       0  235.77      .1       0
Bank Sta=225.9,235.77
XS Rating Curve= 0 ,0
Exp/Cntr(USF)=0,0
Exp/Cntr=0.3,0.1

Type RM Length L Ch R = 1 ,4231    ,293,296,297.7
XS GIS Cut Line= 2
1640810.84662538557104.5447458211641208.92908145 556966.74381821
#Sta/Elev= 30
       0  890.01     8.3  885.79    23.1  880.31      37  876.25    54.4  866.95
    82.1     849      96  841.06     103  837.99   113.4  835.09   126.1  828.56
   151.6  819.65     155  818.01   163.1  812.57   175.9  801.71   179.3  795.75
   182.8   788.4   186.3  782.72  190.09779.8981   193.2  779.02  210.58779.8975
   214.1  781.91     221  788.92   224.5   790.8   241.8  794.75   259.2  800.87
   300.8  812.49   346.8  833.79   387.5  847.85   401.5  856.28   421.3  864.71
#Mann= 3 ,-1,0
       0      .1       0  190.09    .045       0  210.58      .1       0
Bank Sta=190.09,210.58
XS Rating Curve= 0 ,0
Exp/Cntr(USF)=0,0
Exp/Cntr=0.3,0.1

Type RM Length L Ch R = 1 ,3935    ,207.3,197.7,188.8
XS GIS Cut Line= 3
1640811.01324892557283.9649500811641058.27521592557307.240396906
1641310.11226083557291.117014423
#Sta/Elev= 30
       0  913.35    28.4  903.59    71.2  885.06    94.3  876.66   110.7  868.78
   127.2  858.44   143.7  845.74   170.1  831.27   183.2  821.64   196.4  808.82
   222.8  787.27   232.7  784.69   239.6  780.59   249.1  776.98   265.6  775.56
   277.4771.6548   285.3  770.81  295.42 771.657   298.4  772.43   308.3   780.7
     328  792.81   349.1  798.93   360.9  804.57   383.9  818.04   406.9  826.54
   426.7  836.69   456.3  846.28   463.4  850.35     476  860.04   500.7  874.03
#Mann= 3 ,-1,0
       0      .1       0   277.4    .045       0  295.42      .1       0
Bank Sta=277.4,295.42
XS Rating Curve= 0 ,0
Exp/Cntr(USF)=0,0
Exp/Cntr=0.3,0.1

Type RM Length L Ch R = 1 ,3737    ,225,228,230.3
XS GIS Cut Line= 3
1641045.88114296557712.5260240641641187.92095853557392.349153672
1641312.24047937557301.888713761
#Sta/Elev= 30
       0  893.26    34.6  878.08    67.8  861.67    94.2  846.65   139.6  825.74
   168.8  806.22   198.7  791.21   208.6  784.82   218.6  779.68   233.5  774.56
     236  772.95   240.9  767.93  245.23766.1232   253.4   764.8  262.05766.1238
   268.8  769.31   272.4  769.79   310.5  771.72   322.6  773.59   353.2  773.71
   362.1  775.96   385.7  790.91   416.1  813.02   422.2  818.18   439.6  835.21
   445.9  840.01   458.4  845.96   465.4  850.22   480.2  861.28     504  873.45
#Mann= 3 ,-1,0
       0      .1       0  245.23    .045       0  262.05      .1       0
Bank Sta=245.23,262.05
XS Rating Curve= 0 ,0
Exp/Cntr(USF)=0,0
Exp/Cntr=0.3,0.1

Type RM Length L Ch R = 1 ,3509    ,146.7,148.1,148.6
XS GIS Cut Line= 2
1641209.41958849557786.6353989691641472.31258878557393.132511455
#Sta/Elev= 30
       0  886.28     6.3  884.29    21.6  872.96    58.3  852.19    91.4  836.74
   120.3  819.17     136  805.49   157.6   791.9   175.5  783.93   195.9  772.52
   203.1  769.77   226.8  765.64   249.9  764.93  259.13761.5812   274.1   760.8
  286.36761.5807   290.1   763.1   297.8  770.53   301.9  773.14   325.8  783.71
   341.2  796.03   349.2  800.74   368.8  808.94   388.6  820.37   415.5  830.59
   435.9  839.83   447.8  843.12   455.7  846.55   462.8  851.18   473.2     860
#Mann= 3 ,-1,0
       0      .1       0  259.13    .045       0  286.36      .1       0
Bank Sta=259.13,286.36
XS Rating Curve= 0 ,0
Exp/Cntr(USF)=0,0
Exp/Cntr=0.3,0.1