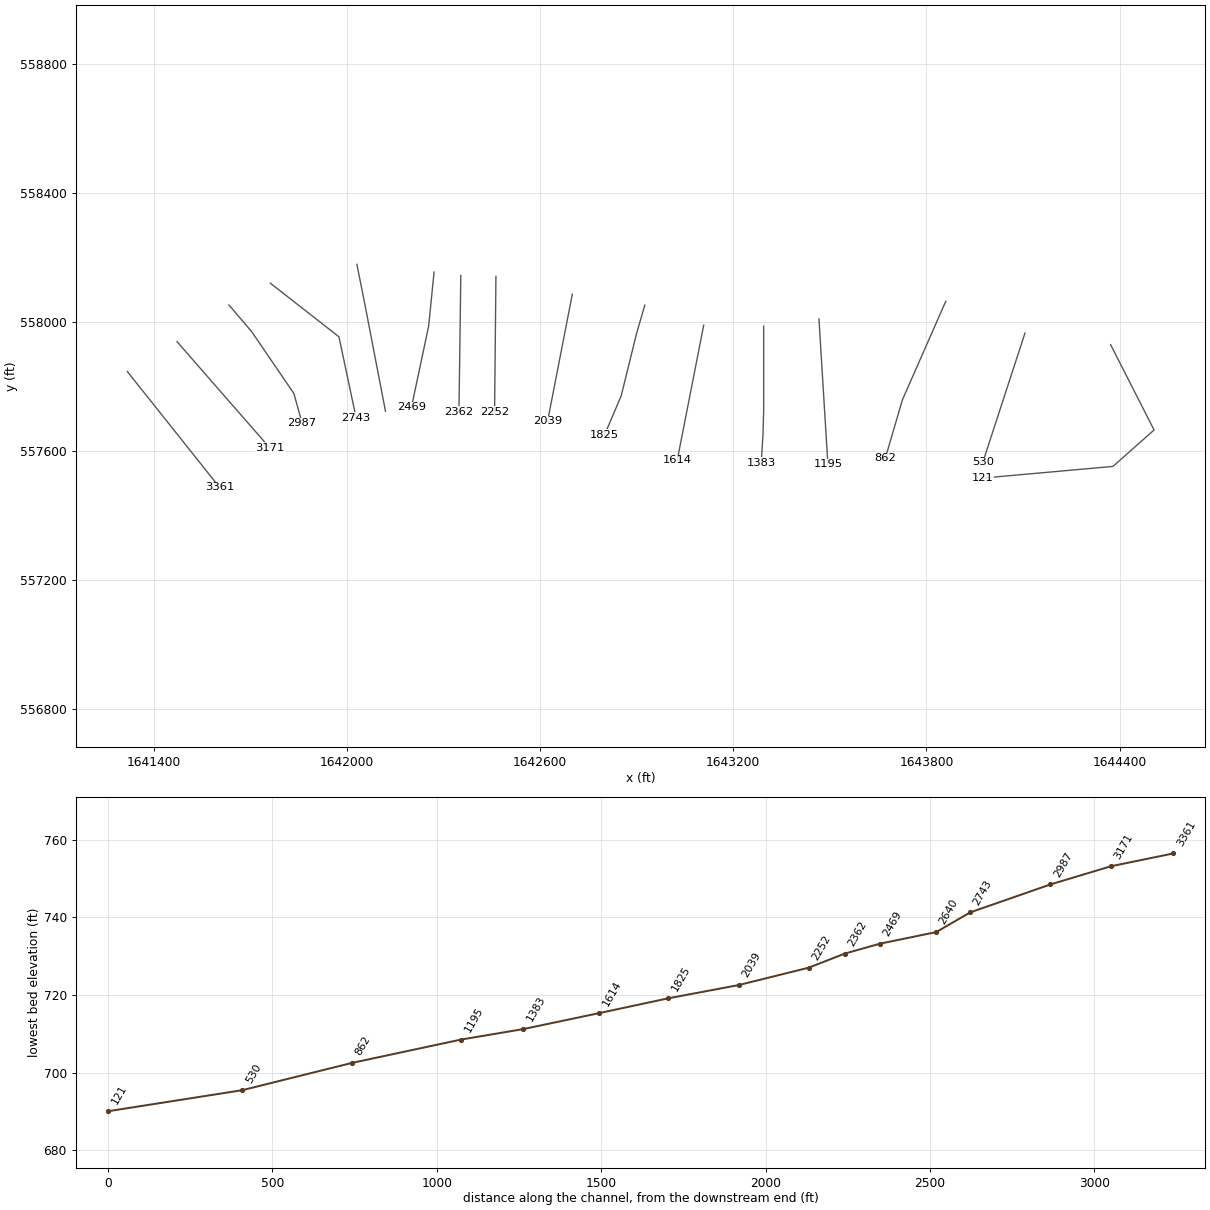
HEC-RAS study JakesRn.prj: JakesRn

--- JakesRn.g01 (geometry) --- (continued)

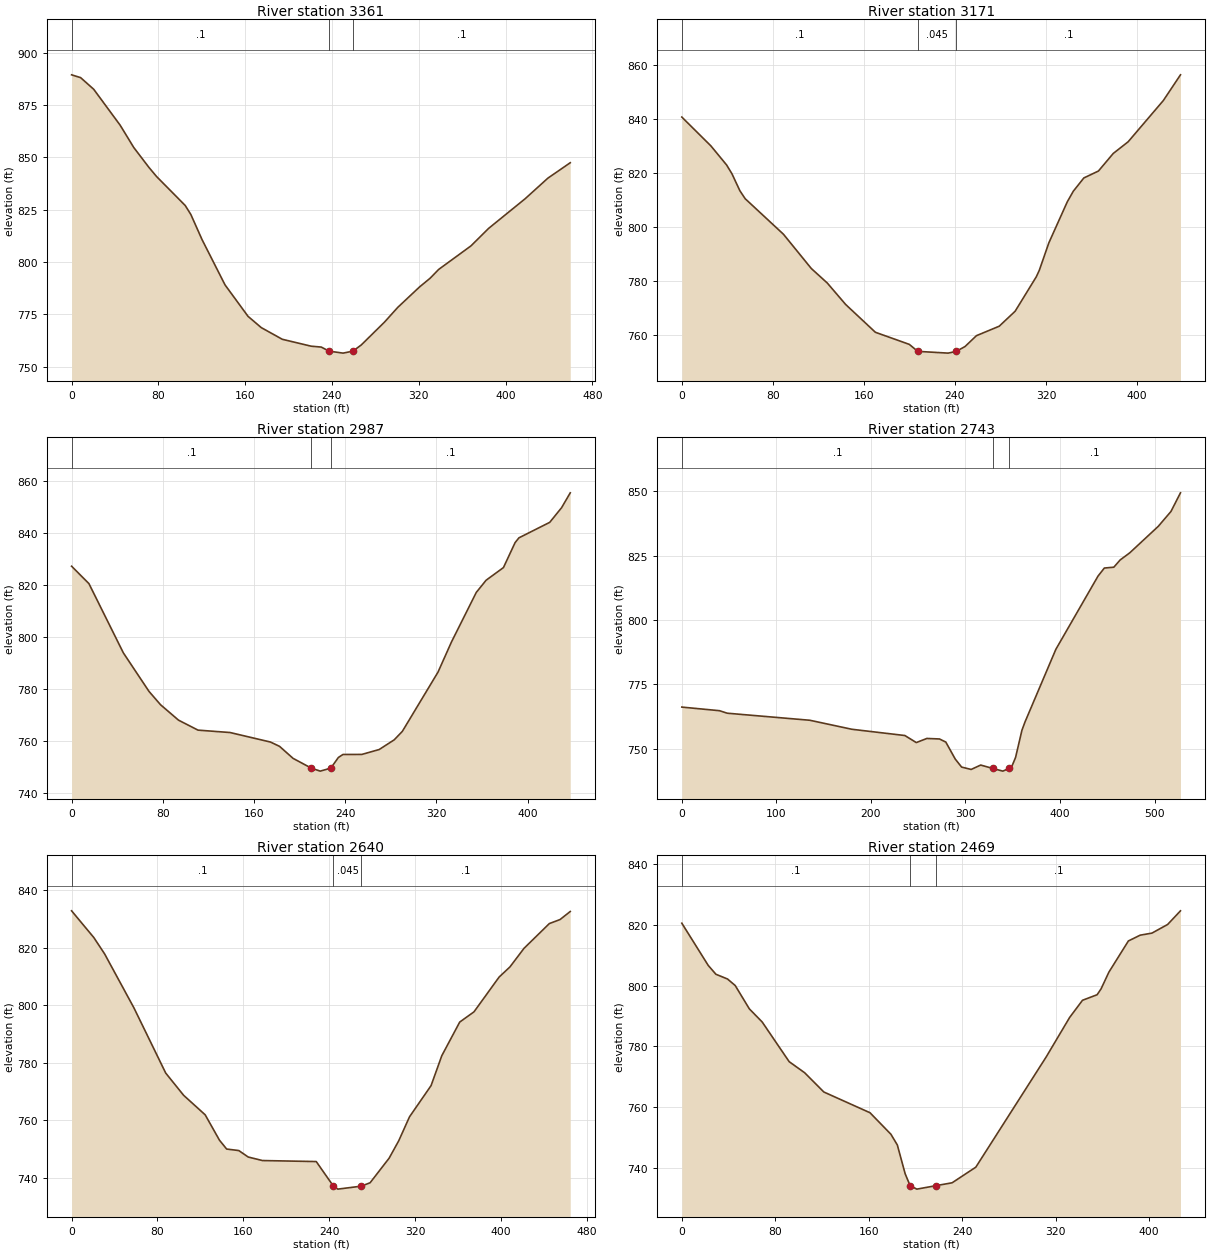
Type RM Length L Ch R = 1 ,3361    ,189.6,190.2,190.9
XS GIS Cut Line= 2
1641318.68150598557846.3495635331641604.85131804557486.764459377
#Sta/Elev= 30
       0  889.34     8.3     888    20.4  882.43    44.8  865.25    57.3  854.63
    71.3  845.11    78.3  840.78   104.7  826.95   109.9  822.65   120.3  810.58
   141.4  789.03   162.6  774.01   174.8  768.62   194.2  763.04   220.8  759.74
   230.1  759.32  237.31 757.381   250.2  756.43   259.3757.3828     267  760.34
   288.5   771.3   300.6  778.27   320.7  788.04   330.5  792.22   338.3  796.39
   368.1  807.65   384.4  816.02     418  830.15   438.9  839.96   459.6  847.36
#Mann= 3 ,-1,0
       0      .1       0  237.31    .045       0   259.3      .1       0
Bank Sta=237.31,259.3
XS Rating Curve= 0 ,0
Exp/Cntr(USF)=0,0
Exp/Cntr=0.3,0.1

Type RM Length L Ch R = 1 ,3171    ,185,183.9,181.4
XS GIS Cut Line= 2
 1641472.7754588557939.4395430361641760.97013631557609.313399182
#Sta/Elev= 30
       0  840.76    25.5  830.08    39.4  822.95    44.1  819.67      51  813.42
    55.7  810.44    89.3  797.26   113.8  784.53   127.8  779.16     144  771.17
   170.1  760.86   199.9  756.37  207.34753.7747     234  753.12  241.19753.7746
   248.9  755.58   258.9   759.6   278.9  763.11   292.9  768.67   311.5  781.46
   314.1  783.82   322.5  794.03   338.7  809.26     344  813.22   353.3  818.16
   366.1  820.72   379.1  827.24   392.2  831.58   423.1  846.88   438.2  856.44
#Mann= 3 ,-1,0
       0      .1       0  207.34    .045       0  241.19      .1       0
Bank Sta=207.34,241.19
XS Rating Curve= 0 ,0
Exp/Cntr(USF)=0,0
Exp/Cntr=0.3,0.1

Type RM Length L Ch R = 1 ,2987    ,245.4,244.4,238.6
XS GIS Cut Line= 4
1641633.99634253558053.3350449631641704.83141703557970.099251818
1641835.81618943557778.2272520661641861.31686708557685.868193418
#Sta/Elev= 30
       0  827.17    15.2  820.49    45.4  793.88    67.9  779.07      78  773.96
    93.8  768.02   110.9  764.19     139  763.27   174.4  759.62   182.4  757.96
   194.3  753.33  210.29749.5938   218.1  748.44  227.35749.5922     234  753.68
     238  754.83   254.6  754.86   269.8  756.74     283  760.47   290.1  763.71
   321.4  786.48   333.3  798.15     355  817.12   363.6  821.79   378.8  826.65
     389  836.23   392.4  838.08   419.4  844.03   429.8  849.66   437.4  855.37
#Mann= 3 ,-1,0
       0      .1       0  210.29    .045       0  227.35      .1       0
Bank Sta=210.29,227.35
XS Rating Curve= 0 ,0
Exp/Cntr(USF)=0,0
Exp/Cntr=0.3,0.1

Type RM Length L Ch R = 1 ,2743    ,101.8,103,99
XS GIS Cut Line= 3
  1641762.593618558120.8736788561641975.68108712557954.399093599
1642028.95295441557703.022469861
#Sta/Elev= 30
       0  766.12    39.8  764.72    48.1  763.74   135.4     761   179.8   757.5
   235.9  755.07     248  752.33   259.2  753.93   272.5  753.73   279.2  752.53
   289.2  745.91   295.9  742.81     306  741.88   316.1  743.59  328.77  742.29
   339.5  741.23  346.12 742.285   349.6  743.56     353  746.56   359.7   757.1
     363  760.37   395.6  788.58   440.2  817.04   446.9  820.17   456.9  820.49
   463.6  823.31   473.7  826.06   503.9  836.37   517.3  842.14   527.4   849.4
#Mann= 3 ,-1,0
       0      .1       0  328.77    .045       0  346.12      .1       0
Bank Sta=328.77,346.12
XS Rating Curve= 0 ,0
Exp/Cntr(USF)=0,0
Exp/Cntr=0.3,0.1

Type RM Length L Ch R = 1 ,2640    ,173.1,170.8,163.8
XS GIS Cut Line= 3
1642031.36873578558179.4071481531642054.98372255 558061.44333152
1642120.16619234 557723.28736127
#Sta/Elev= 30
       0  832.77    20.7   823.5    30.8   817.8    58.1  799.08    87.7  776.46
   104.4  768.74   124.5  761.96   137.8  753.16   144.5  750.08   155.8  749.56
   164.6  747.31   177.9  746.09     228  745.74  243.98737.2122   248.1  736.17
  270.15 737.212   278.2  738.39   295.9  746.91   304.9  752.98   314.9  761.27
     335  772.11     345  782.49   361.7  794.16     375  797.71   398.4  809.78
   408.5   813.3   421.6  819.75   445.2  828.34   455.2  829.75   464.7  832.54
#Mann= 3 ,-1,0
       0      .1       0  243.98    .045       0  270.15      .1       0
Bank Sta=243.98,270.15
XS Rating Curve= 0 ,0
Exp/Cntr(USF)=0,0
Exp/Cntr=0.3,0.1

Type RM Length L Ch R = 1 ,2469    ,105.2,107,110.6
XS GIS Cut Line= 3
1642271.11935116558155.3448210621642254.20038698557987.414854839
1642200.71475194557734.942389048
#Sta/Elev= 30
       0  820.46    22.6  806.61    29.2   803.7    39.1  802.15    45.7  800.01
    57.8  792.35    68.8  788.04    91.9  775.02   105.1   771.4   121.6  765.06
   161.1  758.26     179   751.2   184.5  747.68   191.2  738.23  195.44734.3265
   201.2  733.19  217.67734.3286   231.4  735.27   251.7   740.4   311.9  776.55
     332  789.52     343  795.16   355.5  796.98   358.9  798.89   365.6  804.39
   382.3  814.63   392.4  816.53   402.5  817.21   415.9  820.04   426.9  824.52
#Mann= 3 ,-1,0
       0      .1       0  195.44    .045       0  217.67      .1       0
Bank Sta=195.44,217.67
XS Rating Curve= 0 ,0
Exp/Cntr(USF)=0,0
Exp/Cntr=0.3,0.1

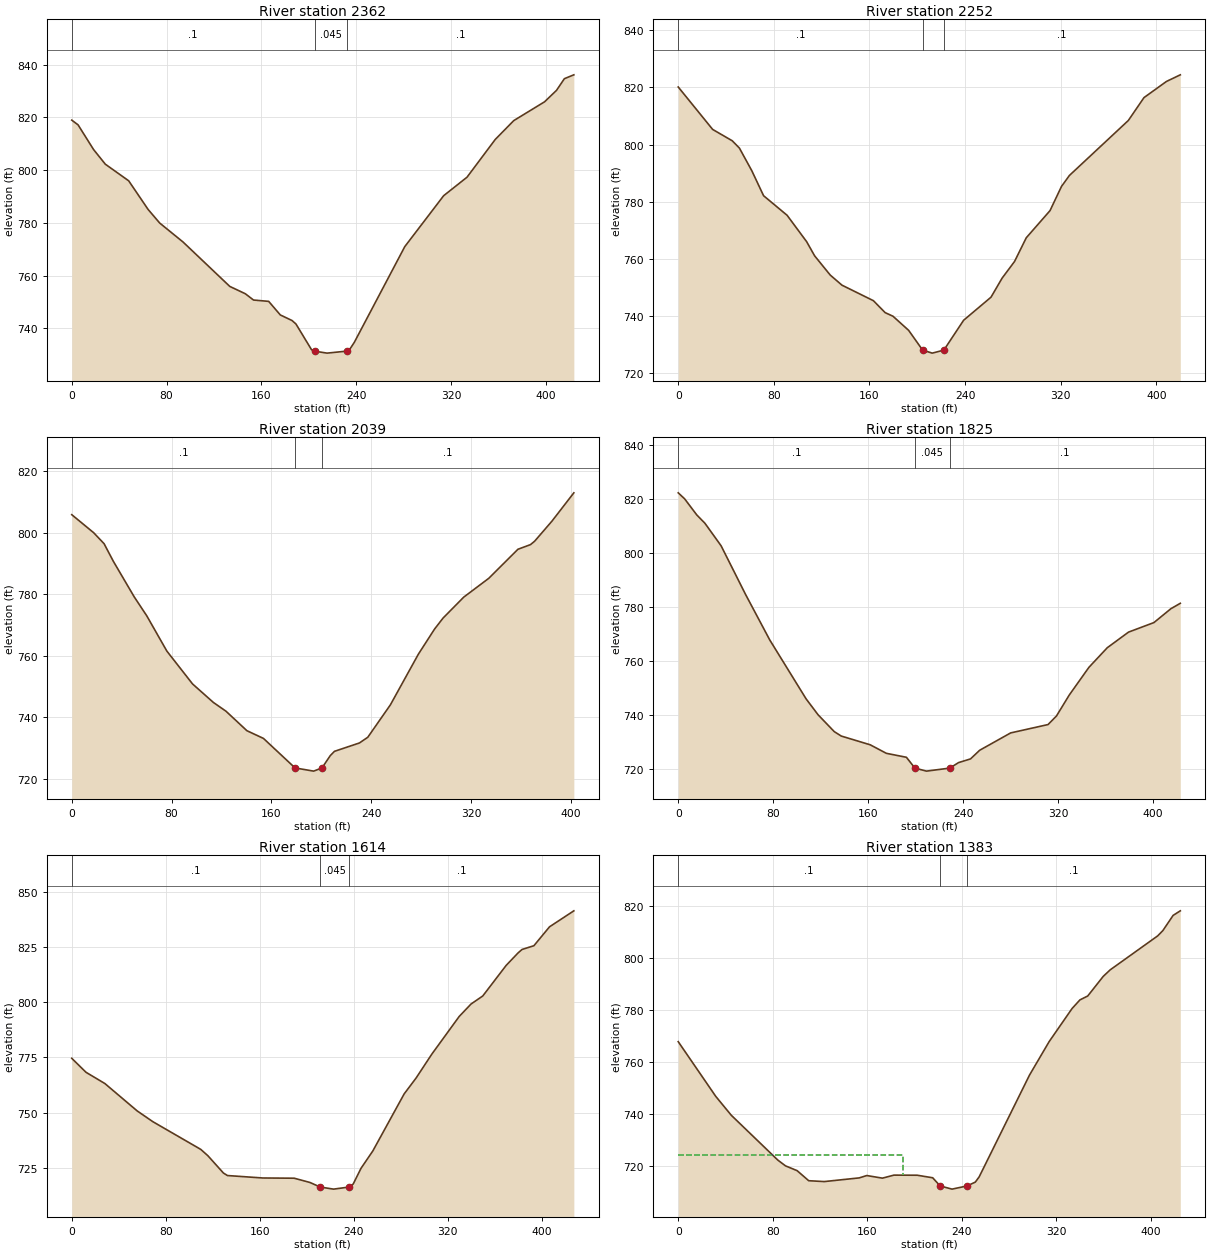
Type RM Length L Ch R = 1 ,2362    ,110,110.2,110.5
XS GIS Cut Line= 2
1642354.11148517558144.6966720821642348.36483398557721.200622262
#Sta/Elev= 30
       0  818.97     5.3  817.19    18.4  807.82    28.3  802.27      48  795.98
    64.4  785.11    74.2  779.95    93.9  772.75   133.3  755.93   146.4  753.15
   153.3  750.77   166.1  750.26   175.9  745.12   185.8     743   189.1  741.69
   202.2  731.97  204.76731.3959   215.3  730.64  231.87731.3967     235  732.44
   238.3  734.71   280.9  771.02   313.7  790.33   333.4  797.34   357.2  811.64
   372.8  818.79   398.8  825.92   408.9  830.27   415.5  834.68   423.5  836.15
#Mann= 3 ,-1,0
       0      .1       0  204.76    .045       0  231.87      .1       0
Bank Sta=204.76,231.87
XS Rating Curve= 0 ,0
Exp/Cntr(USF)=0,0
Exp/Cntr=0.3,0.1

Type RM Length L Ch R = 1 ,2252    ,212.8,212.7,209.8
XS GIS Cut Line= 2
1642463.17873148558141.9096495111642459.01686686557721.801785027
#Sta/Elev= 30
       0  820.16    28.8  805.31    45.2  801.33    51.2  798.77    61.6  790.82
    71.4  782.11    91.1  775.25   107.5  765.98   114.1  761.07   127.2  754.32
     137  750.79   163.3  745.36   173.1  741.19   179.7  739.91   192.8  734.97
   204.5728.0515   212.5     727  222.25728.0485   238.8  738.51   261.7  746.58
     271  753.25   281.4  759.08   291.2  767.37   311.1  776.89   320.7  785.36
   327.3  789.19   376.6  808.43   389.7  816.44   408.5   822.1   420.1  824.42
#Mann= 3 ,-1,0
       0      .1       0   204.5    .045       0  222.25      .1       0
Bank Sta=204.5,222.25
XS Rating Curve= 0 ,0
Exp/Cntr(USF)=0,0
Exp/Cntr=0.3,0.1

Type RM Length L Ch R = 1 ,2039    ,214.9,214.3,214.2
XS GIS Cut Line= 2
1642700.37330357558086.7943624771642623.52506431  557691.9047933
#Sta/Elev= 30
       0  805.94    17.5  800.09    25.9   796.5    33.3  790.79      50  779.24
    60.1  773.04    76.2  761.57    96.8  750.88   113.5  744.86   123.6  742.01
   140.3  735.69   153.6  733.17  178.91723.5743   193.8  722.53  200.52723.5728
   207.1  727.56   210.5  728.97   230.5  731.69   237.2  733.55   255.3  744.09
   277.7  760.55   290.7  768.74   297.5  772.31   314.1  779.13   334.1  785.23
   357.5  794.69   367.6  796.21   370.9  797.32   384.7  803.81   402.3  813.05
#Mann= 3 ,-1,0
       0      .1       0  178.91    .045       0  200.52      .1       0
Bank Sta=178.91,200.52
XS Rating Curve= 0 ,0
Exp/Cntr(USF)=0,0
Exp/Cntr=0.3,0.1

Type RM Length L Ch R = 1 ,1825    ,209.7,211,210.1
XS GIS Cut Line= 4
1642925.50041827558052.6816573581642899.48310318557963.132209231
1642852.21254194557770.967101558 1642800.4468786557649.767543837
#Sta/Elev= 30
       0  822.26     5.4  820.03    15.6  814.08    22.5  810.97    36.1  802.64
    56.6   784.7    77.1  767.73   107.7   745.9   117.8     740   131.4  733.77
   137.3  732.12   161.7  728.88   175.3  725.72   192.2  724.25  199.36720.2462
   209.1  719.12  228.74720.2467   236.1  722.28   246.2  723.65   253.9  726.85
     280  733.28   311.5  736.38   318.6  739.56   329.3  747.28   345.9  757.57
   361.4  764.86   379.3  770.64   400.7  774.18     415  779.32   422.9  781.32
#Mann= 3 ,-1,0
       0      .1       0  199.36    .045       0  228.74      .1       0
Bank Sta=199.36,228.74
XS Rating Curve= 0 ,0
Exp/Cntr(USF)=0,0
Exp/Cntr=0.3,0.1

Type RM Length L Ch R = 1 ,1614    ,228.3,230.7,232.9
XS GIS Cut Line= 2
1643108.41047448557990.5279607231643026.20080275557571.258634891
#Sta/Elev= 30
       0   774.6    12.1  768.27    28.2  763.15    55.6  750.78      69  745.87
   109.8   733.3   115.8  730.46   129.1  722.57   132.5  721.45   162.6  720.34
   189.3  720.24   202.7  718.31  211.49716.2273   222.8  715.29  235.87716.2266
   239.5  717.59   246.2  724.75   256.2  732.58   282.9  758.47     293  765.62
   306.3  776.39   329.7  793.55   339.8  799.21   349.8  802.86   369.7  816.72
   379.9  822.41   383.2  823.94   393.3  825.64   406.6  834.21   427.3  841.46
#Mann= 3 ,-1,0
       0      .1       0  211.49    .045       0  235.87      .1       0
Bank Sta=211.49,235.87
XS Rating Curve= 0 ,0
Exp/Cntr(USF)=0,0
Exp/Cntr=0.3,0.1

Type RM Length L Ch R = 1 ,1383    ,187.4,188.1,188.8
XS GIS Cut Line= 6
1643294.55980216557987.4478692551643294.55980216557899.948044255
1643294.55980216 557824.948194251643294.55980216557724.948066174
1643292.44628933557649.9478880911643286.98829499 557562.44806309
#Sta/Elev= 30
       0  767.82    31.8   746.8    44.9  739.57    84.3  722.35    90.8  720.13
   100.7  718.27   110.5  714.41   123.7  714.08   153.2  715.49   159.7   716.4
   172.9   715.4   182.7  716.56   202.4  716.52   215.5  715.54  221.79712.4066
   231.9  711.18  244.64712.4088   251.6  713.88   254.9  715.93   297.5     755
   314.1  767.83   333.6   780.6   340.2  783.88   346.8  785.37   359.9  792.89
   365.8  795.41     406  808.45   410.4  810.48   419.1  816.33   425.2  818.09
#Mann= 3 ,-1,0
       0      .1       0  221.79    .045       0  244.64      .1       0
#XS Ineff= 2 , 0
          190.61  724.13
Permanent Ineff=
       F       F
Bank Sta=221.79,244.64
XS Rating Curve= 0 ,0
Exp/Cntr(USF)=0,0
Exp/Cntr=0.3,0.1

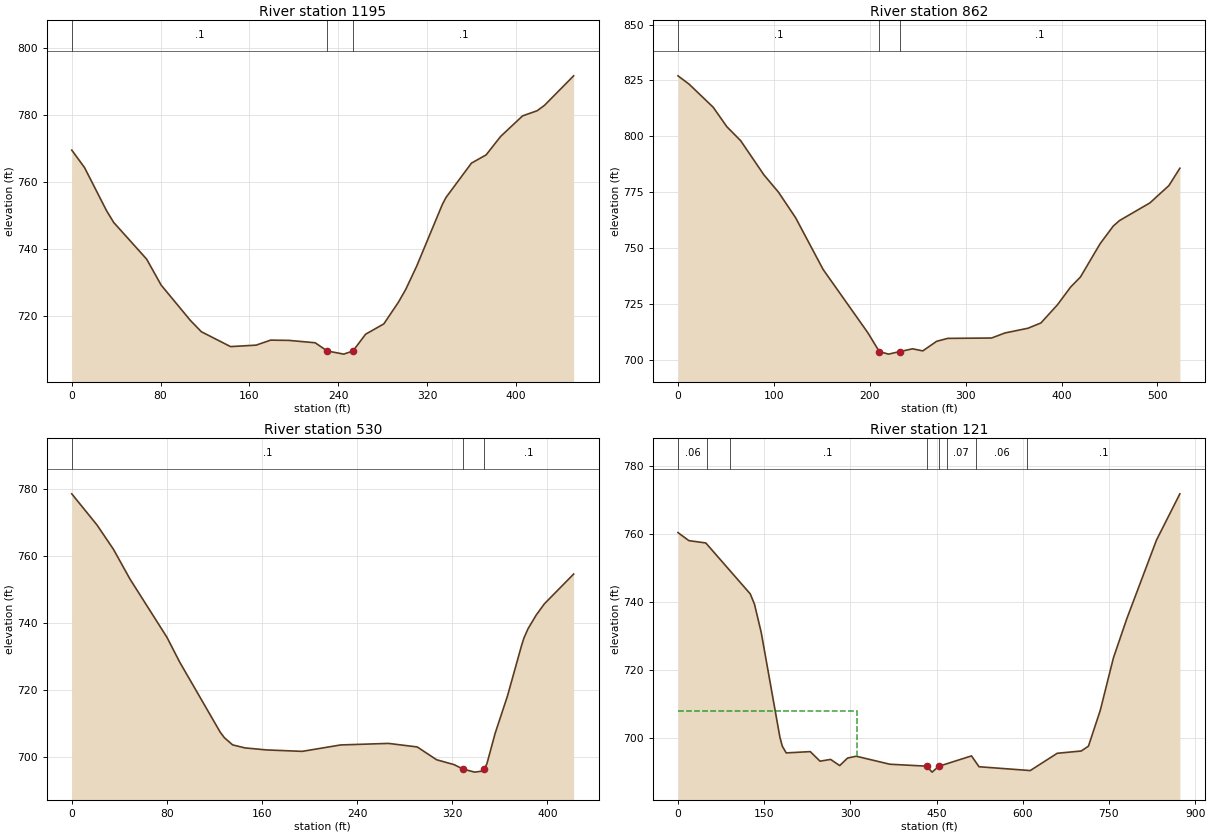
Type RM Length L Ch R = 1 ,1195    ,334.9,332.9,325
XS GIS Cut Line= 2
1643466.30897523558009.7952533111643493.96333377557558.694056023
#Sta/Elev= 30
       0  769.55    11.5  764.33    31.2   751.5    37.8  747.89    67.4  736.94
    80.5  729.16   106.8  718.59   116.7   715.2     143  710.75     166  711.19
   179.1  712.69   195.6  712.61   219.2   711.9     230709.4484   244.9   708.5
  253.23 709.449   264.6  714.46     281  717.55   294.2  724.07   300.8  727.91
   310.6  734.84   333.6  753.22   336.9  755.34   359.9  765.66   373.1  768.12
   386.2  773.65   405.9  779.79   419.1  781.34   425.7  782.96   451.9  791.78
#Mann= 3 ,-1,0
       0      .1       0     230    .045       0  253.23      .1       0
Bank Sta=230,253.23
XS Rating Curve= 0 ,0
Exp/Cntr(USF)=0,0
Exp/Cntr=0.3,0.1

Type RM Length L Ch R = 1 ,862     ,329.9,332.4,330.1
XS GIS Cut Line= 3
1643860.10916593558064.7101856071643725.54545518557758.897417874
1643672.32857462557577.286749876
#Sta/Elev= 30
       0  827.05    11.6  823.31    36.7  812.99      51  804.25    65.4     798
    89.6  782.72   104.8  774.97   122.7   763.5   151.4  740.34     198  712.04
  209.92 703.644   219.5  702.47   231.8703.6456   244.6  704.85   255.3  703.92
   269.7   708.2   281.3  709.52     327  709.68     341  711.94     365  714.06
   378.5  716.43   395.7  724.53   409.4  732.46   419.7  736.98   440.2  751.88
   453.9  759.77   460.4  762.24   492.2  770.18     512  777.93   523.4  785.68
#Mann= 3 ,-1,0
       0      .1       0  209.92    .045       0   231.8      .1       0
Bank Sta=209.92,231.8
XS Rating Curve= 0 ,0
Exp/Cntr(USF)=0,0
Exp/Cntr=0.3,0.1

Type RM Length L Ch R = 1 ,530     ,413.6,408.9,402.1
XS GIS Cut Line= 2
1644106.08801821557966.0515051411643975.19906223557564.855931659
#Sta/Elev= 30
       0   778.7    21.3  769.35    35.1  762.09    48.9  753.25      80  735.82
    90.8  728.35   124.8  707.44   128.3  705.78   135.2  703.63   145.5  702.72
   163.7  702.11   193.8  701.68   226.2   703.6   266.3  704.06   290.5     703
   306.8  699.17   321.5  697.71     329696.3834   338.8  695.47   345.7   695.8
   346.8696.3857   349.1  697.99     356  707.07   366.4  718.27   378.1  733.19
   380.2  735.57   383.6  738.31   390.5  742.43   397.4   745.8     422   754.7
#Mann= 3 ,-1,0
       0      .1       0     329    .045       0   346.8      .1       0
Bank Sta=329,346.8
XS Rating Curve= 0 ,0
Exp/Cntr(USF)=0,0
Exp/Cntr=0.3,0.1

Type RM Length L Ch R = 1 ,121     ,,,
XS GIS Cut Line= 4
1644371.99640828557929.8986876981644506.95779689557664.967117002
1644379.16458458557551.829089585 1643975.3593028557515.677170235
#Sta/Elev= 30
       0  760.33      19  757.97    48.4  757.29   125.7  742.36   133.1  739.33
   144.8  731.07   177.3  700.34   181.4  697.71   188.3  695.68   230.2  696.06
   247.2  693.25   265.6  693.77   281.4  691.96   295.1  694.17   310.2  694.71
   368.6  692.36   432.5  691.79   442.2  690.04   453.8  691.75   510.8   694.8
   523.9  691.62     613   690.5     660  695.57   701.8  696.24   714.3  697.66
   734.8  708.12   757.8  723.58   780.9  734.98   832.6  758.09   873.4  771.71
#Mann= 8 ,-1,0
       0     .06       0      50     .07       0      90      .1       0
   432.5    .045       0   453.8      .1       0  467.33     .07       0
  518.01     .06       0  608.01      .1       0
#XS Ineff= 2 , 0
          311.48  707.92
Permanent Ineff=
       F       F
Bank Sta=432.5,453.8
XS Rating Curve= 0 ,0
Exp/Cntr(USF)=0,0
Exp/Cntr=0.3,0.1
LCMann Table=0

Chan Stop Cuts=-1
Use User Specified Reach Order=0
Composite Channel Slope=5